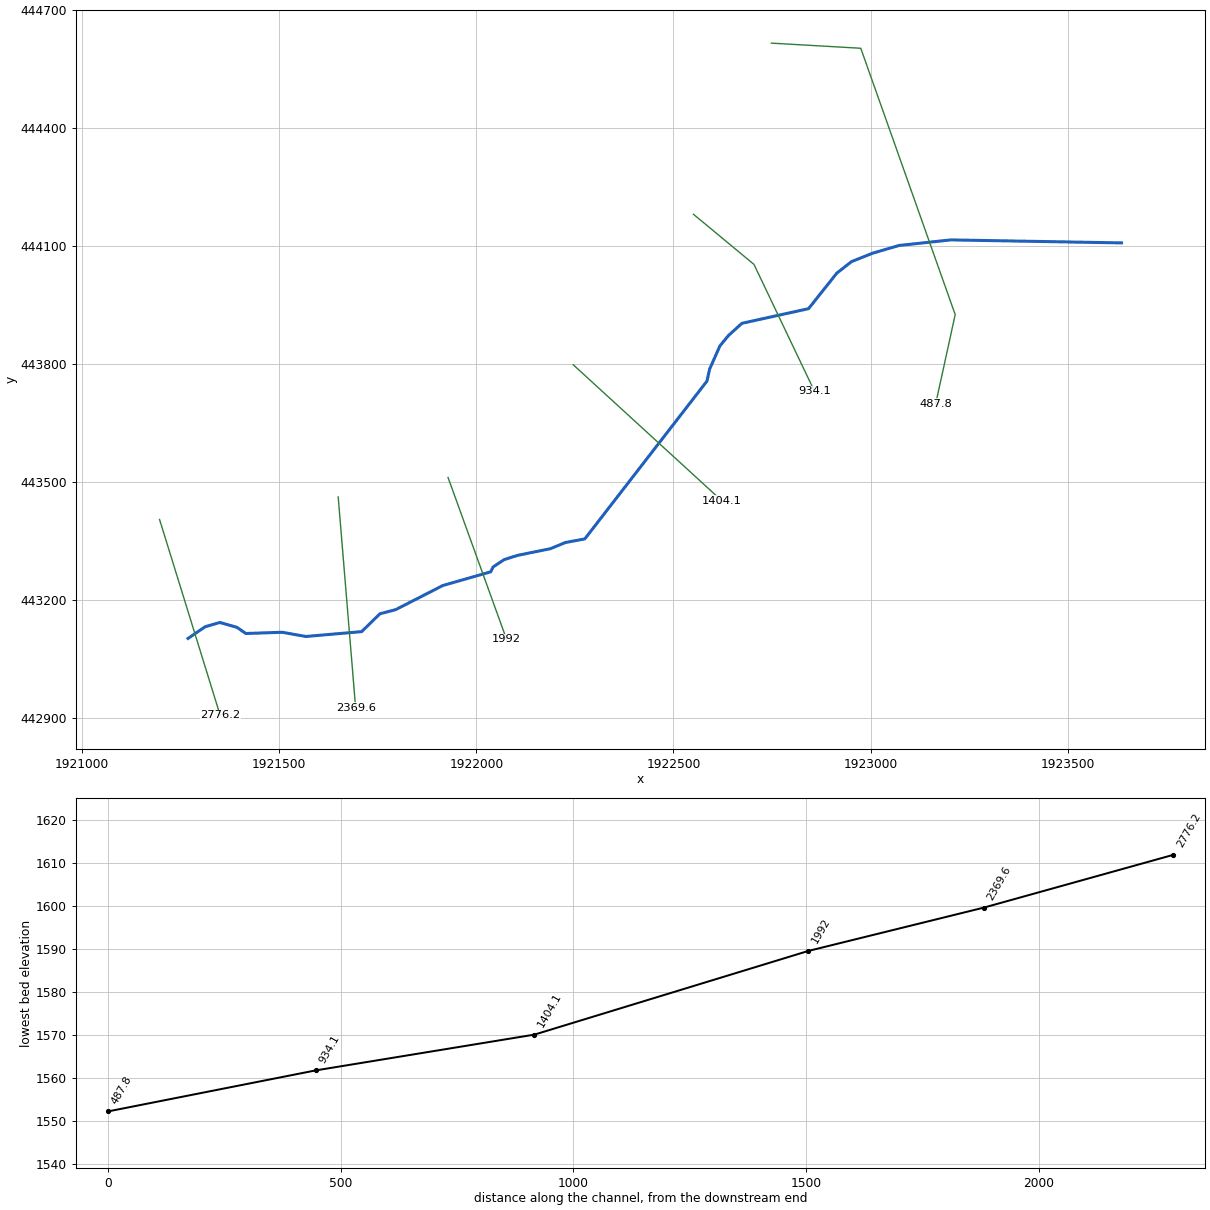
--- NP6.prj (project) ---

Proj Title=NP6
Current Plan=p01
Geom File=g01
Flow File=f01
Plan File=p01
DSS Export Rating Curves=0
DSS Export Rating Curve Sorted=0
DSS Export Volume Flow Curves=0
DXF OffsetX=0
DXF OffsetY=0
DXF ScaleX=0
DXF ScaleY=0

--- NP6.p01 (plan) ---

Plan Title=Floodplain
Program Version=4.00
Geom File=g01
Flow File=f01
K Sum by GR=0
Std Step Tol=0.01
Critical Tol=0.01
Num of Std Step Trials=20
Max Error Tol=0.3
Flow Tol Ratio=0.001
Split Flow NTrial=30
Split Flow Tol=0.02
Split Flow Ratio=0.02
Log Output Level=0
Friction Slope Method=1
Unsteady Friction Slope Method=2
Unsteady Bridges Friction Slope Method=1
Global Log Level=0
CheckData=False
Run HTab=0
Run UNet=0
Run PostProcess=0
UNET Theta=0
UNET Theta Warmup=0
UNET ZTol=0
UNET ZSATol=0
UNET MxIter=0
UNET MaxInSteps=0
UNET DtIC=0
UNET DtMin=0
UNET MaxCRTS=0
UNET WFStab=0
UNET SFStab=0
UNET WFX=0
UNET SFX=0
UNET DSS MLevel=0
UNET DZMax Abort=0
UNET Convert EG Bridges=0
UNET Use Existing IB Tables=0
UNET Froude Limit=0
UNET Froude Power=0
Write IC File=0
Echo Input=False
Echo Output=False
Write Detailed=0

--- NP6.f01 (steady flow) ---

Flow Title=NFF Regression Equation
Program Version=4.10
Number of Profiles= 1
Profile Names=P100yr
River Rch & RM=NP6,Main            ,2776.2
563.2677
River Rch & RM=NP6,Main            ,934.1
592.1922
Boundary for River Rch & Prof#=NP6,Main            , 1
Up Type= 0
Dn Type= 3
Dn Slope=0.02166
DSS Import GetInterval= 0
DSS Import GetPeak= 0
DSS Import FillOption= 0

--- NP6.g01 (geometry) ---

Geom Title=USGS 10m DEM
Program Version=4.10

River Reach=NP6             ,Main
Reach XY= 30
     1921268.629      443101.462      1921312.17      443131.178
     1921349.388      443142.034      1921392.81      443129.627
     1921415.091      443114.031      1921507.52      443117.101
     1921567.618      443106.417     1921709.167      443118.772
     1921755.379      443164.055     1921795.621      443174.741
      1921915.26       443236.08     1922036.379      443270.748
     1922042.582      443283.154     1922070.496      443301.763
     1922104.613      443312.618     1922188.354      443329.677
     1922225.573      443345.184     1922275.198      443354.489
     1922585.028      443755.583     1922591.554      443785.603
     1922617.917      443845.153     1922639.628      443871.516
     1922673.745      443902.531     1922842.779       443939.75
     1922914.114      444029.694     1922951.333      444059.159
      1923005.61       444080.87     1923072.404       444100.37
     1923203.345      444114.541     1923636.585      444106.899

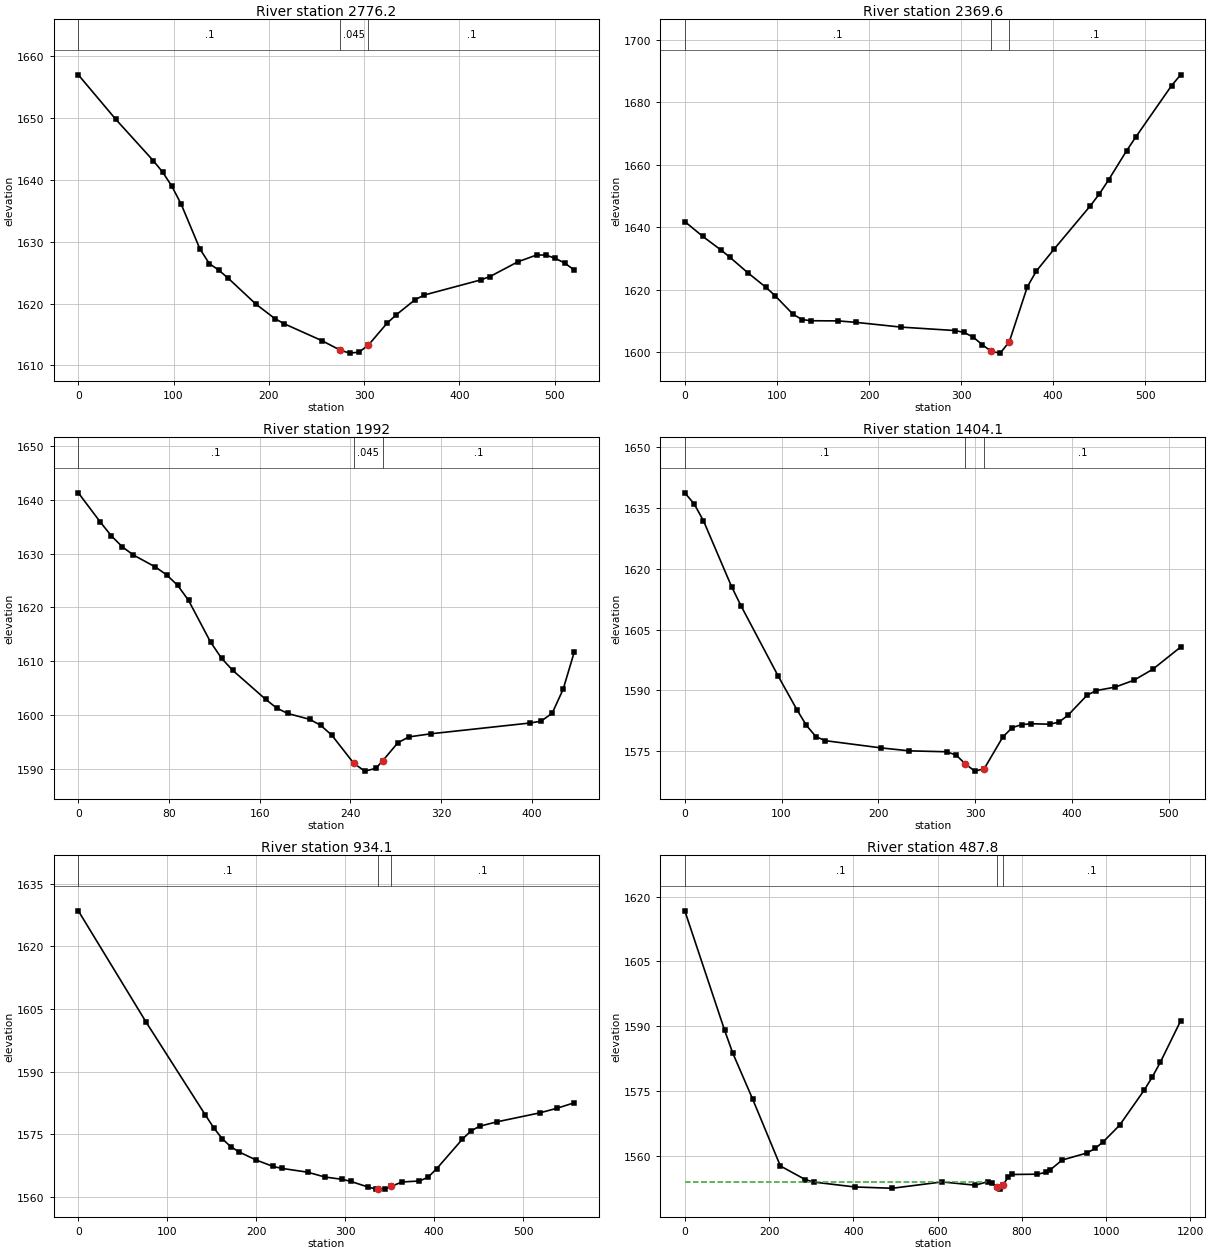
Type RM Length L Ch R = 1 ,2776.2  ,411,406.6,402.2
XS GIS Cut Line= 2
      1921196.48      443403.774     1921350.126      442906.378
#Sta/Elev= 30
       0 1656.98    39.3 1649.79    78.6 1643.12    88.4 1641.28    98.2 1638.97
     108 1636.06   127.7 1628.82   137.5 1626.47   147.3 1625.42   157.2 1624.12
   186.6 1619.89   206.3 1617.58   216.1 1616.74   255.4 1614.03     275 1612.47
   284.8 1611.99   294.7 1612.15   304.5 1613.28   324.1 1616.82     334 1618.21
   353.6 1620.63   363.4 1621.39   422.4 1623.82   432.2 1624.37   461.6 1626.76
   481.3 1627.86   491.1 1627.84   500.9  1627.3   510.8 1626.54   520.6 1625.43
#Mann= 3 , 0 , 0
       0      .1       0     275    .045       0   304.5      .1       0
Bank Sta=275,304.5
XS Rating Curve= 0 ,0
Exp/Cntr=0.3,0.1

Type RM Length L Ch R = 1 ,2369.6  ,371.3,377.6,383.9
XS GIS Cut Line= 2
     1921649.605      443461.065     1921693.876      442924.607
#Sta/Elev= 30
       0 1641.81    19.6 1637.04    39.2 1632.73    48.9  1630.4    68.5 1625.41
    88.1 1620.77    97.9 1618.12   117.4 1612.19   127.2 1610.46     137 1610.08
   166.4 1610.03     186 1609.56   234.9 1608.04   293.6 1606.94   303.4 1606.32
   313.2 1604.81     323 1602.42   332.8 1600.26   342.5 1599.72   352.3 1603.36
   371.9 1620.95   381.7    1626   401.3 1633.12   440.4 1646.89   450.2 1650.71
     460 1655.09   479.6 1664.44   489.4 1668.76   528.5 1685.31   538.3 1688.75
#Mann= 3 , 0 , 0
       0      .1       0   332.8    .045       0   352.3      .1       0
Bank Sta=332.8,352.3
XS Rating Curve= 0 ,0
Exp/Cntr=0.3,0.1

Type RM Length L Ch R = 1 ,1992    ,575.2,587.9,600
XS GIS Cut Line= 2
     1921928.251      443510.545     1922076.689      443099.086
#Sta/Elev= 30
       0 1641.26    19.4 1635.83    29.2 1633.26    38.9 1631.22    48.6 1629.72
      68  1627.5    77.8 1626.05    87.5 1624.13    97.2 1621.31   116.6 1613.58
   126.4 1610.55   136.1 1608.34   165.2 1602.95     175 1601.32   184.7 1600.32
   204.1 1599.23   213.8 1598.12   223.6 1596.29     243 1591.07   252.7 1589.62
   262.4 1590.13   268.6 1591.57   281.9 1594.89   291.6 1595.97     311 1596.55
   398.5 1598.55   408.2 1598.89     418 1600.36   427.7 1604.82   437.4 1611.66
#Mann= 3 , 0 , 0
       0      .1       0     243    .045       0   268.6      .1       0
Bank Sta=243,268.6
XS Rating Curve= 0 ,0
Exp/Cntr=0.3,0.1

Type RM Length L Ch R = 1 ,1404.1  ,478.9,470,461.3
XS GIS Cut Line= 2
      1922245.96      443797.003     1922623.564      443450.649
#Sta/Elev= 30
       0 1638.63     9.7 1635.89    19.3 1631.75    48.3 1615.58      58 1610.87
    96.7 1593.46     116 1585.22   125.7  1581.4   135.4 1578.67     145 1577.66
     203 1575.87     232 1575.15   270.7 1574.92   280.4 1574.11     290 1571.91
   299.7 1570.16   309.4 1570.74   328.7 1578.58   338.4 1580.86     348 1581.59
   357.7 1581.82     377  1581.7   386.7 1582.21   396.4    1584   415.7 1588.84
   425.4 1589.99   444.7 1590.83     464 1592.51   483.4 1595.18   512.4 1600.68
#Mann= 3 , 0 , 0
       0      .1       0     290    .045       0   309.4      .1       0
Bank Sta=290,309.4
XS Rating Curve= 0 ,0
Exp/Cntr=0.3,0.1

Type RM Length L Ch R = 1 ,934.1   ,448,446.3,444.3
XS GIS Cut Line= 3
     1922550.647      444179.815     1922704.293      444052.211
     1922857.939      443729.295
#Sta/Elev= 30
       0 1628.53    76.1 1601.88   142.7 1579.62   152.2 1576.52   161.7 1573.92
   171.2 1572.03   180.7 1570.74   199.7 1568.82     219 1567.26   228.7  1566.8
   257.7 1565.89     277 1564.74   296.4 1564.18     306  1563.7   325.4 1562.35
     335 1561.83   336.6 1561.84   344.7 1561.92   351.6  1562.5     364 1563.55
   383.4 1563.78     393 1564.67   402.7  1566.7   431.7 1573.81   441.4 1575.79
     451  1576.9   470.4 1577.95   518.7 1580.11     538 1581.21   557.3 1582.52
#Mann= 3 , 0 , 0
       0      .1       0   336.6    .045       0   351.6      .1       0
Bank Sta=336.6,351.6
XS Rating Curve= 0 ,0
Exp/Cntr=0.3,0.1

Type RM Length L Ch R = 1 ,487.8   ,495.6,487.8,479.3
XS GIS Cut Line= 4
     1922748.564      444614.711     1922975.126       444601.69
      1923214.71      443924.607      1923165.23      443698.045
#Sta/Elev= 30
       0 1616.72    94.6 1589.04   113.5 1583.86   160.8 1573.19   226.9 1557.64
     286 1554.49   305.6 1553.92     404 1552.78   492.6 1552.48   610.6 1553.95
   689.4 1553.19   718.9 1553.99   728.7  1553.8   740.7 1552.67   748.4 1552.28
   755.7 1553.26   768.1 1555.15   777.9 1555.67   836.9 1555.74   856.6 1556.14
   866.4 1556.66     896 1559.02   954.8 1560.65   974.2 1561.71   993.5 1563.25
  1032.1 1567.06  1090.1 1575.13  1109.4 1578.17  1128.8 1581.63  1177.1 1591.23
#Mann= 3 , 0 , 0
       0      .1       0   740.7    .045       0   755.7      .1       0
#XS Ineff= 2 , 0
          718.06 1554.02
Permanent Ineff=
       F       F
Bank Sta=740.7,755.7
XS Rating Curve= 0 ,0
Exp/Cntr=0.3,0.1

Chan Stop Cuts=-1
Use User Specified Reach Order=0
Composite Channel Slope=5